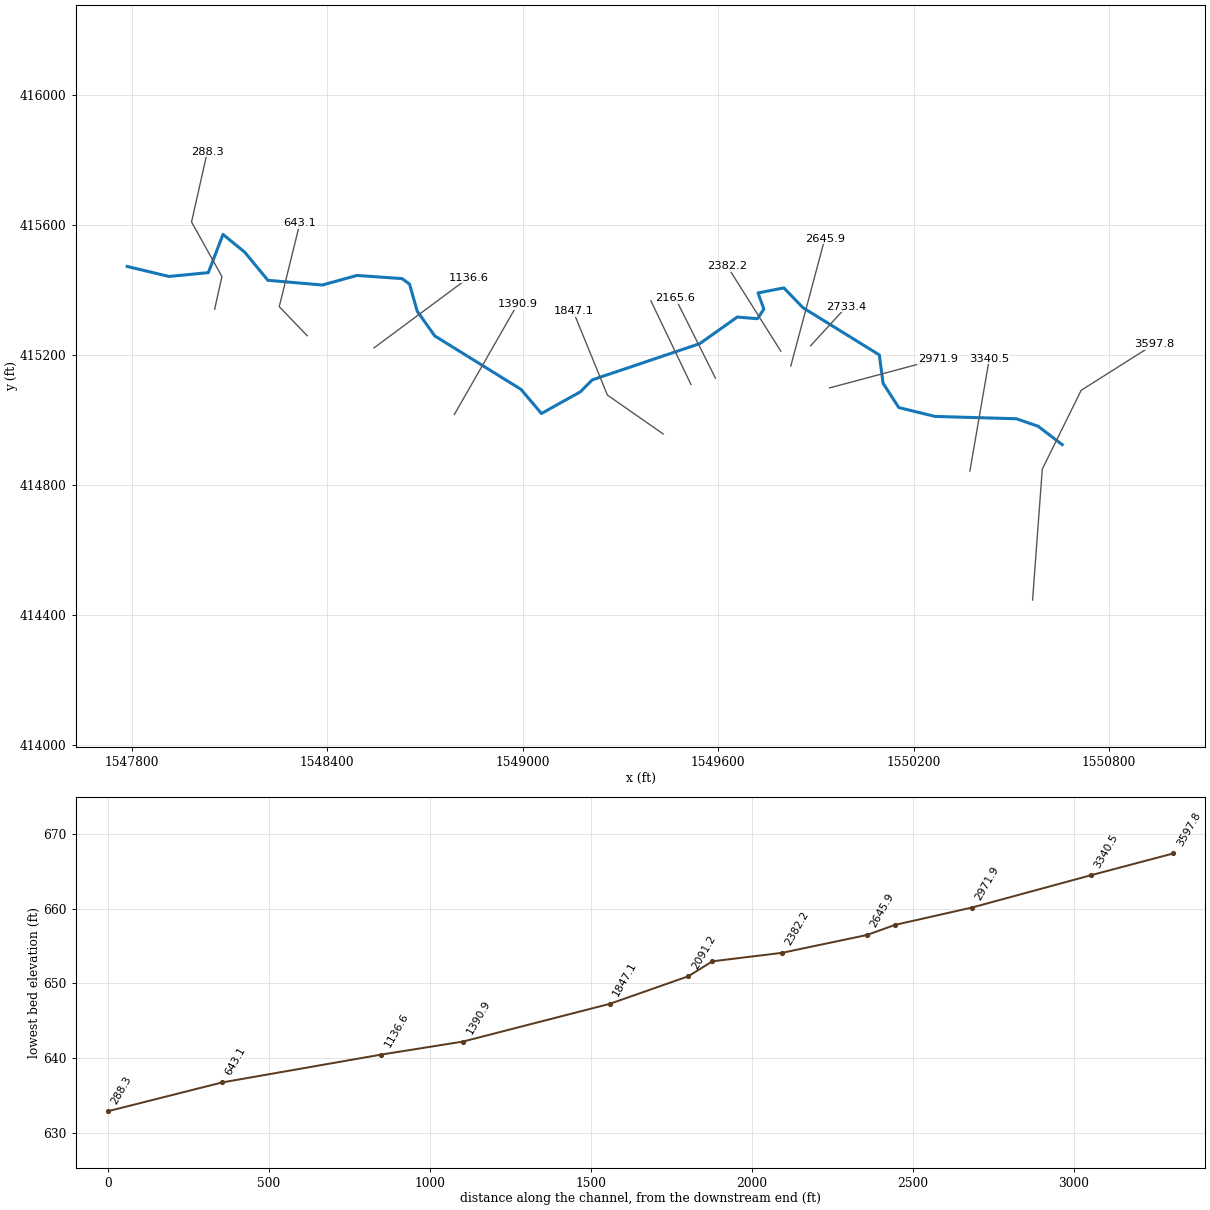
--- SYCAMREBR.prj (project) ---

Proj Title=SYCAMREBR
Current Plan=p01
Default Exp/Contr=0,0
English Units
Geom File=g01
Flow File=f01
Plan File=p01
BEGIN DESCRIPTION:
END DESCRIPTION:
DSS Export Rating Curves= 0
DSS Export Rating Curve Sorted= 0
DSS Export Volume Flow Curves= 0
DXF OffsetX= 0
DXF OffsetY= 0
DXF ScaleX= 0
DXF ScaleY= 0

--- SYCAMREBR.p01 (plan) ---

Plan Title=Floodplain
Program Version=4.00
Geom File=g01
Flow File=f01
K Sum by GR=0
Std Step Tol=0.01
Critical Tol=0.01
Num of Std Step Trials=20
Max Error Tol=0.3
Flow Tol Ratio=0.001
Split Flow NTrial=30
Split Flow Tol=0.02
Split Flow Ratio=0.02
Log Output Level=0
Friction Slope Method=1
Unsteady Friction Slope Method=2
Unsteady Bridges Friction Slope Method=1
Global Log Level=0
CheckData=False
Run HTab=0
Run UNet=0
Run PostProcess=0
UNET Theta=0
UNET Theta Warmup=0
UNET ZTol=0
UNET ZSATol=0
UNET MxIter=0
UNET MaxInSteps=0
UNET DtIC=0
UNET DtMin=0
UNET MaxCRTS=0
UNET WFStab=0
UNET SFStab=0
UNET WFX=0
UNET SFX=0
UNET DSS MLevel=0
UNET DZMax Abort=0
UNET Convert EG Bridges=0
UNET Use Existing IB Tables=0
UNET Froude Limit=0
UNET Froude Power=0
Write IC File=0
Echo Input=False
Echo Output=False
Write Detailed=0

--- SYCAMREBR.f01 (steady flow) ---

Flow Title=NFF Regression Equation
Program Version=4.00
Number of Profiles=1
Profile Names=P100yr
River Rch & RM=SYCAMREBR,Main      ,3597.8
365.6120
River Rch & RM=SYCAMREBR,Main      ,2382.2
373.5043
River Rch & RM=SYCAMREBR,Main      ,2091.2
412.1778
River Rch & RM=SYCAMREBR,Main      ,288.3
447.2147
Boundary for River Rch & Prof#=SYCAMREBR,Main      ,1
Up Type=0
Dn Type=3
Dn Slope=0.00845

--- SYCAMREBR.g01 (geometry) ---

Geom Title=Geometry
Program Version=4.00

River Reach=SYCAMREBR       ,Main
Reach XY= 30
     1550655.968      414924.953     1550581.932      414981.548
     1550515.468      415004.571     1550265.479      415011.744
     1550154.206      415039.114      1550106.14       415113.68
     1550094.556      415201.011     1549860.198      415346.162
     1549801.444      415407.177     1549722.259      415391.632
     1549740.139      415341.838     1549720.532      415312.414
     1549658.452       415317.48     1549543.311      415235.649
     1549213.399      415124.289     1549176.601       415087.26
      1549057.31      415020.759     1548994.629      415094.946
     1548729.677      415259.561     1548675.945       415335.44
     1548652.421      415418.658     1548629.592      415435.746
     1548490.862      415445.441     1548384.741      415415.977
     1548217.491      415430.518     1548146.616      415516.925
     1548079.773      415571.583     1548034.663      415454.037
     1547913.872      415442.328     1547785.844      415473.104

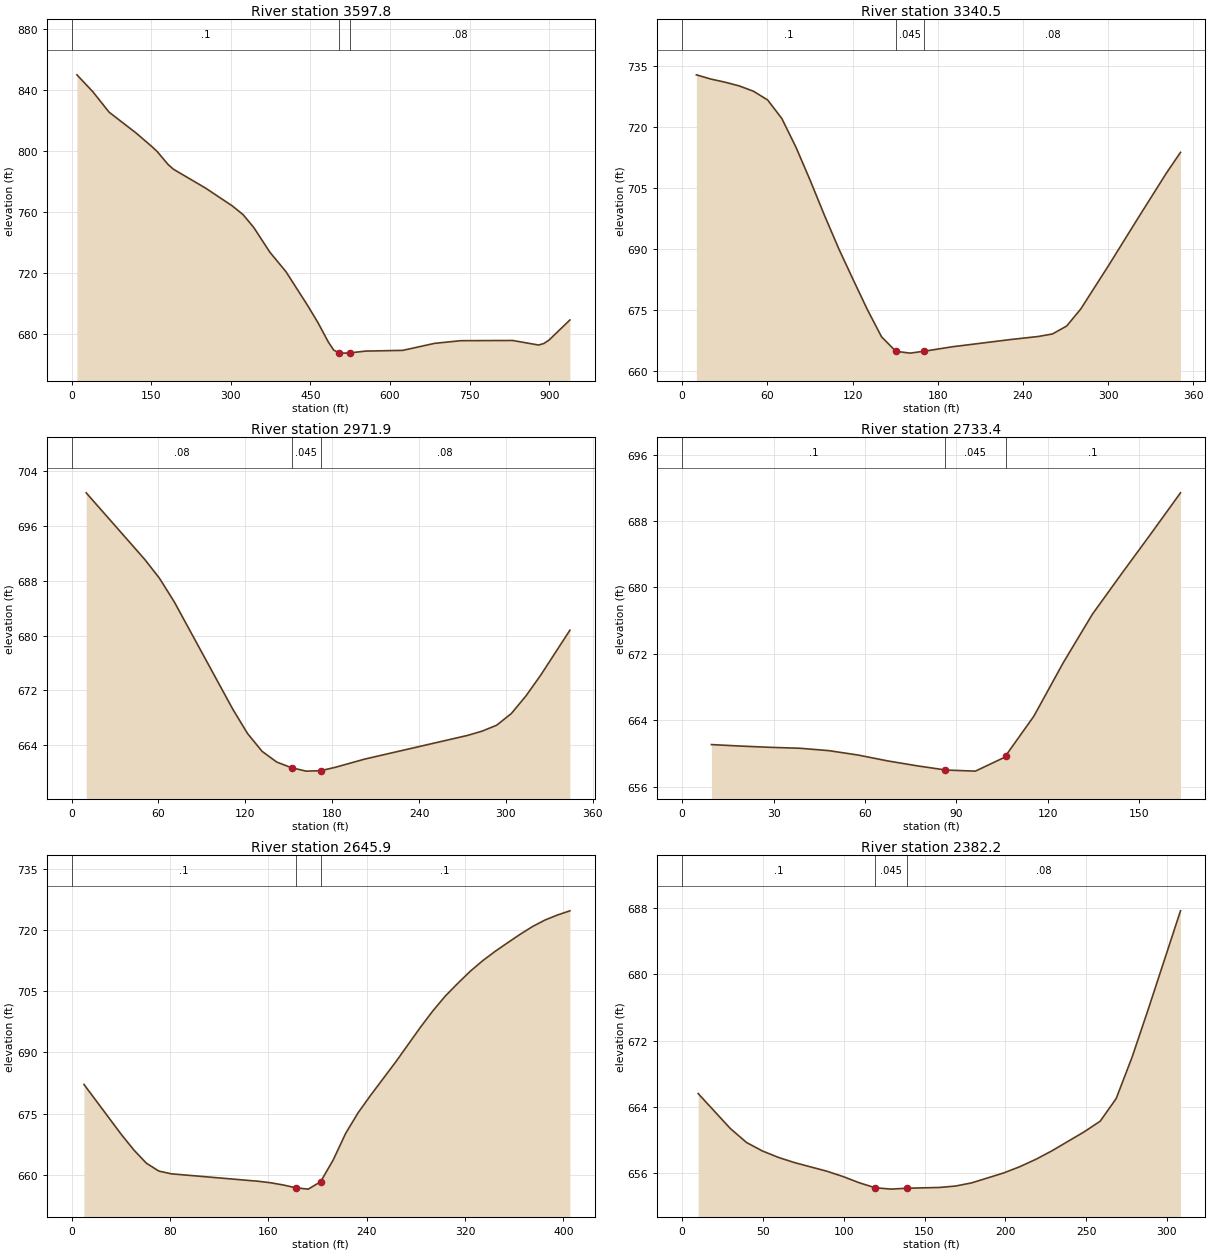
Type RM Length L Ch R = 1 ,3597.8  ,250.1,257.3,264.5
XS GIS Cut Line= 4
     1550565.038      414446.816     1550594.878      414849.652
     1550714.237        415092.1     1550938.034      415233.839
#Sta/Elev= 30
    10.1  850.09    40.4  838.86    70.7  825.58   121.2  812.01   151.5  802.95
   161.6  799.64   181.8  791.27   191.9  788.14   252.5  775.76     303  764.03
   323.2  758.34   343.3  749.92   373.6  733.73   403.9  720.95     444  699.18
     464  687.64     484  674.66     494  669.42     504  667.66     514  667.44
     524  667.59   554.1  668.77   624.1  669.25     684  673.84     733   675.6
   831.2  675.74   880.2  672.75     890  673.76   899.8  676.01   939.1   689.2
#Mann= 3 , 0 , 0
       0      .1       0     504    .045       0     524     .08       0
Bank Sta=504,524
XS Rating Curve= 0 ,0
Exp/Cntr=0.3,0.1

Type RM Length L Ch R = 1 ,3340.5  ,397.1,368.6,340.4
XS GIS Cut Line= 2
      1550372.64      414843.859     1550432.355      415189.755
#Sta/Elev= 27
      10  732.82    20.1  731.79    30.1  731.02    40.1  730.11    50.1  728.81
    60.2  726.65    70.2  722.09    80.2  715.01    90.3   706.8   100.3  698.26
   110.3  690.12   120.3  682.64   130.4  675.22   140.4  668.52   150.5  664.95
   160.5   664.5   170.5  664.97   190.5  666.07   230.7  667.81   250.7  668.58
   260.8   669.2   270.8  671.15   280.8  675.36   300.9  686.32   320.9  697.54
     341  708.66     351  713.79
#Mann= 3 , 0 , 0
       0      .1       0   150.5    .045       0   170.5     .08       0
Bank Sta=150.5,170.5
XS Rating Curve= 0 ,0
Exp/Cntr=0.3,0.1

Type RM Length L Ch R = 1 ,2971.9  ,223.6,238.5,253.2
XS GIS Cut Line= 2
     1549942.134       415099.56     1550274.617      415188.628
#Sta/Elev= 20
    10.1  700.87    50.6  691.12    60.7  688.38    70.9  684.94   111.4  669.22
   121.5  665.69   131.6  663.07   141.7  661.51     152  660.67     162  660.18
     172  660.24   182.2  660.74   202.5  661.94   273.3  665.39   283.5  666.02
   293.6  666.89   303.7  668.59   313.8  671.16     324   674.2   344.2  680.78
#Mann= 3 , 0 , 0
       0     .08       0     152    .045       0     172     .08       0
Bank Sta=152,172
XS Rating Curve= 0 ,0
Exp/Cntr=0.3,0.1

Type RM Length L Ch R = 1 ,2733.4  ,75.3,87.5,99.9
XS GIS Cut Line= 2
     1549883.653       415229.19     1549994.069      415349.746
#Sta/Elev= 19
     9.6  661.06    19.2  660.88    28.8  660.73    38.5  660.62    48.1  660.33
    57.7   659.8    67.3   659.1    76.9  658.51    86.2  658.01    86.5  657.99
    96.2  657.86   105.8  659.53   106.2  659.74   115.4  664.49     125  670.91
   134.6  676.78   144.2  681.67   153.9  686.53   163.5  691.41
#Mann= 3 , 0 , 0
       0      .1       0    86.2    .045       0   106.2      .1       0
Bank Sta=86.2,106.2
XS Rating Curve= 0 ,0
Exp/Cntr=0.3,0.1

Type RM Length L Ch R = 1 ,2645.9  ,232.5,263.6,284.2
XS GIS Cut Line= 2
     1549822.775      415166.699     1549927.214      415558.345
#Sta/Elev= 30
    10.1  682.14    40.5  669.88    50.7  666.08    60.8  662.86    70.9  660.93
    81.1  660.25     152  658.42   162.1  658.05   172.3  657.51   182.5  656.82
   192.5   656.5   202.5  658.29   212.8  663.66   222.9  670.15   233.1  675.23
   243.2  679.48   263.5   687.6   283.7  696.14   293.9  700.19     304  703.81
   314.1  706.91   324.3  709.88   334.4  712.47   344.5  714.75   354.7  716.87
   364.8  718.92   374.9  720.83   385.1  722.43   395.2  723.66   405.3  724.68
#Mann= 3 , 0 , 0
       0      .1       0   182.5    .045       0   202.5      .1       0
Bank Sta=182.5,202.5
XS Rating Curve= 0 ,0
Exp/Cntr=0.3,0.1

Type RM Length L Ch R = 1 ,2382.2  ,219.3,216.6,213.4
XS GIS Cut Line= 2
       1549792.1      415212.592     1549627.981       415473.69
#Sta/Elev= 25
     9.9  665.62    29.8  661.41    39.8  659.73    49.7   658.7    59.7  657.92
    69.6   657.3    89.5  656.27    99.5  655.63   109.4  654.89   119.3  654.28
   129.3  654.11   139.3  654.22   159.2  654.31   169.1  654.48   179.1  654.86
     199  656.06   208.9  656.81   218.9   657.7   228.8  658.72   248.7     661
   258.7  662.29   268.6  665.02   278.5  670.04   288.5  675.81   308.4  687.63
#Mann= 3 , 0 , 0
       0      .1       0   119.3    .045       0   139.3     .08       0
Bank Sta=119.3,139.3
XS Rating Curve= 0 ,0
Exp/Cntr=0.3,0.1

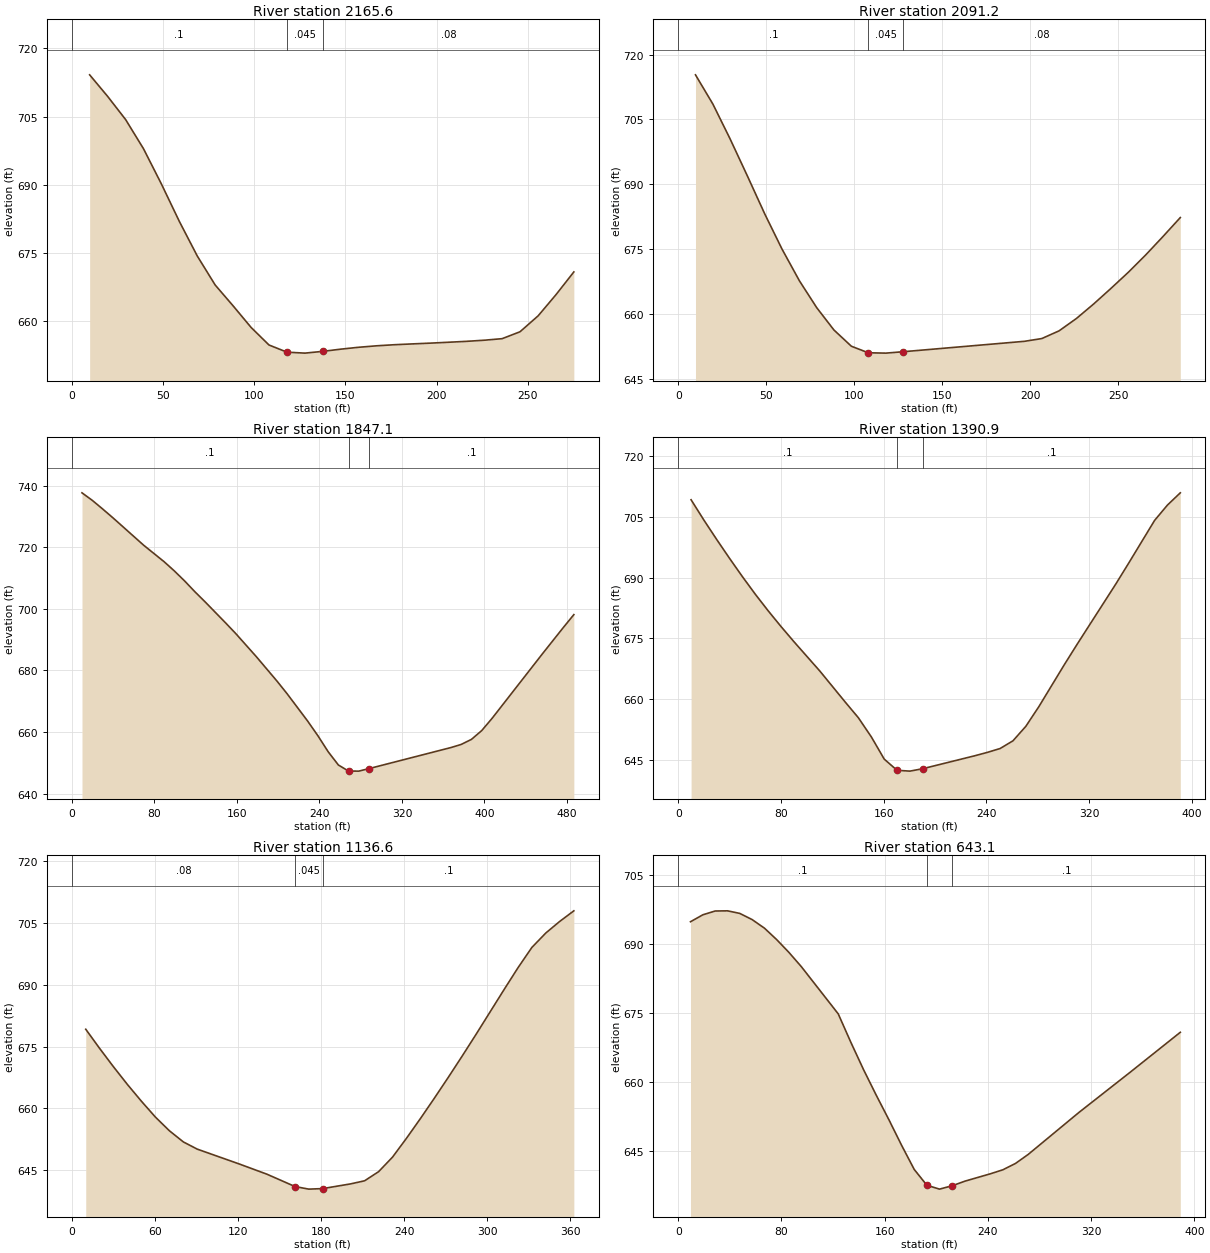
Type RM Length L Ch R = 1 ,2165.6  ,74.8,74.4,74
XS GIS Cut Line= 2
     1549591.518        415129.4     1549468.429      415375.577
#Sta/Elev= 30
     9.8  714.18    19.7  709.42    29.5  704.35    39.3  697.94    49.1   690.2
      59  681.91    68.8  674.33    78.6  667.96    88.5  663.34    98.3  658.62
   108.1  654.76   117.8  653.21     118  653.18   127.8  652.97   137.6  653.36
   137.8  653.37   147.4  653.84   157.3  654.26   167.1  654.58   176.9  654.82
   186.8     655   196.6  655.17   206.4  655.36   216.3  655.56   226.1  655.81
   235.9  656.15   245.7  657.67   255.6  661.16   265.4  665.82   275.2  670.83
#Mann= 3 , 0 , 0
       0      .1       0   117.8    .045       0   137.8     .08       0
Bank Sta=117.8,137.8
XS Rating Curve= 0 ,0
Exp/Cntr=0.3,0.1

Type RM Length L Ch R = 1 ,2091.2  ,245.5,244,242.6
XS GIS Cut Line= 2
     1549516.394         415110.     1549393.305      415367.367
#Sta/Elev= 23
     9.8  715.33    19.7  708.56    29.5  700.49    39.4  691.85    49.2  683.13
      59  675.01    68.9  667.67    78.7  661.48    88.5  656.31    98.4  652.56
     108  651.05     118  650.97     128   651.3   196.7   653.7   206.6  654.34
   216.4  656.12   226.3  658.99   236.1  662.35   245.9  665.94   255.8  669.68
   265.6  673.66   275.4  677.91   285.3  682.32
#Mann= 3 , 0 , 0
       0      .1       0     108    .045       0     128     .08       0
Bank Sta=108,128
XS Rating Curve= 0 ,0
Exp/Cntr=0.3,0.1

Type RM Length L Ch R = 1 ,1847.1  ,479.7,456.2,427.8
XS GIS Cut Line= 3
     1549431.129      414957.821     1549259.906      415077.325
     1549155.112      415334.548
#Sta/Elev= 30
     9.9  737.69    19.9  735.24    29.8  732.48    39.8   729.6    69.6  720.69
    89.5  715.31    99.4  712.32   109.4  709.05   119.3  705.56   129.3  702.24
   149.1  695.43   159.1   691.9     179  684.41   198.9  676.52   208.8  672.37
   228.6  663.54   238.6  658.74   248.5  653.57   258.4  649.26   268.2   647.3
   278.2  647.27   288.2   648.1   367.5  654.93   377.4  655.94   387.4  657.59
   397.3  660.44   407.2  664.35   456.8  685.66   476.6  694.01   486.6  698.11
#Mann= 3 , 0 , 0
       0      .1       0   268.2    .045       0   288.2      .1       0
Bank Sta=268.2,288.2
XS Rating Curve= 0 ,0
Exp/Cntr=0.3,0.1

Type RM Length L Ch R = 1 ,1390.9  ,264.7,254.3,244
XS GIS Cut Line= 2
     1548789.937      415017.644     1548983.895      415357.071
#Sta/Elev= 30
      10   709.2      20  704.17    30.1  699.32    40.1  694.67    50.1  690.16
    60.1  685.84    70.2  681.72    80.2  677.84    90.2  674.12   110.3   666.9
   130.3  659.15   140.3  655.37   150.4  650.63   160.4  645.17   170.4  642.41
   180.4  642.21   190.4  642.81   230.6  645.98   240.6  646.83   250.6  647.79
   260.6  649.69   270.6  653.26   280.7  658.09   300.7  668.54   310.7  673.59
   340.8  688.46   350.8   693.6   370.9  704.11   380.9  707.89   390.9  710.91
#Mann= 3 , 0 , 0
       0      .1       0   170.4    .045       0   190.4      .1       0
Bank Sta=170.4,190.4
XS Rating Curve= 0 ,0
Exp/Cntr=0.3,0.1

Type RM Length L Ch R = 1 ,1136.6  ,476,493.5,511
XS GIS Cut Line= 2
     1548543.398      415222.649     1548834.335      415438.987
#Sta/Elev= 30
    10.1  679.18    20.1  674.55    30.2  670.06    40.3  665.76    50.4  661.71
    60.4  657.91    70.5   654.6    80.6  651.89    90.6  650.15   120.9  646.56
     141  644.07   161.2  641.09   171.2  640.46   181.2  640.59   201.4  641.73
   211.5  642.48   221.6  644.69   231.6  648.19   241.7  652.76   251.8  657.55
   261.8  662.45   271.9  667.52     282  672.71   292.1  678.01   312.2  688.78
   322.3  694.09   332.3     699   342.4   702.5   352.5  705.32   362.6  707.86
#Mann= 3 , 0 , 0
       0     .08       0   161.2    .045       0   181.2      .1       0
Bank Sta=161.2,181.2
XS Rating Curve= 0 ,0
Exp/Cntr=0.3,0.1

Type RM Length L Ch R = 1 ,643.1   ,311.1,354.8,372.1
XS GIS Cut Line= 3
      1548338.25      415259.948     1548252.461      415349.467
      1548315.87      415606.835
#Sta/Elev= 29
     9.5  694.78    19.1  696.29    28.6  697.11    38.2  697.15    47.7  696.59
    57.2  695.26    66.8  693.39    76.3   690.9    85.8  688.12    95.4  685.03
     124  674.78   133.8  668.59   143.6  662.68   153.4  657.15   163.3  651.78
   173.1  646.25   182.9     641   192.5  637.64   192.7  637.57   202.5  636.73
   212.5  637.48   222.2  638.46   241.8  640.05   251.6  640.93   261.4  642.31
   271.2  644.26   310.5  653.37   349.8  662.01   389.1  670.78
#Mann= 3 , 0 , 0
       0      .1       0   192.5    .045       0   212.5      .1       0
Bank Sta=192.5,212.5
XS Rating Curve= 0 ,0
Exp/Cntr=0.3,0.1

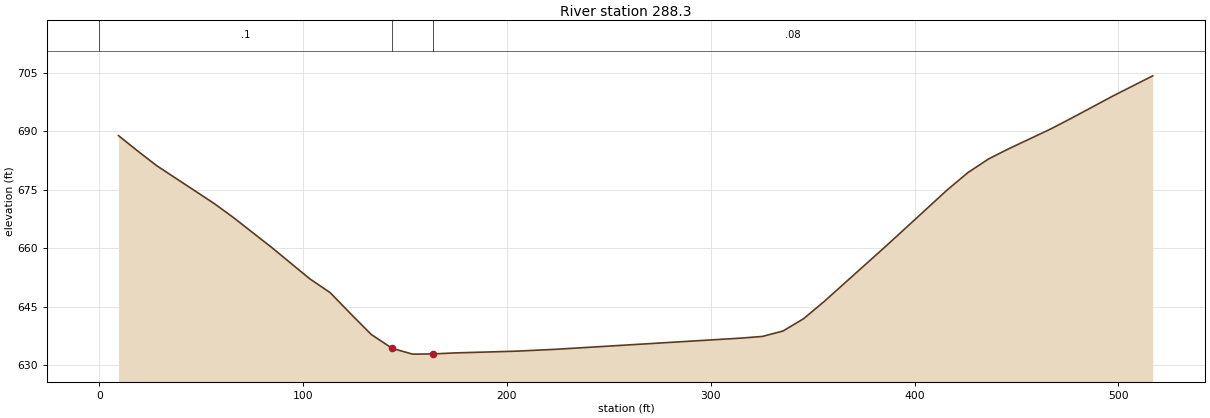
Type RM Length L Ch R = 1 ,288.3   ,305.6,288.3,272.8
XS GIS Cut Line= 4
     1548054.105      415341.401     1548076.485       415442.11
     1547983.236      415609.958     1548031.725      415826.296
#Sta/Elev= 30
     9.4  688.89    18.8  684.95    28.1  681.19    56.3   671.5    65.7  667.92
    84.4  660.29   103.2   652.2   113.3  648.62   123.4  643.18   133.5  637.88
   143.7  634.35   153.7  632.87   163.7  632.92   173.9  633.17   204.2  633.62
   224.4  634.12   315.3  636.99   325.4  637.41   335.5   638.8   345.6  641.96
   355.6  646.33   385.9  660.52   416.1  674.98   426.2   679.4   436.3  682.89
   446.3  685.53   466.5   690.5   476.6  693.23   496.7  698.86   516.9  704.21
#Mann= 3 , 0 , 0
       0      .1       0   143.7    .045       0   163.7     .08       0
Bank Sta=143.7,163.7
XS Rating Curve= 0 ,0
Exp/Cntr=0.3,0.1

Chan Stop Cuts=-1
Use User Specified Reach Order=0